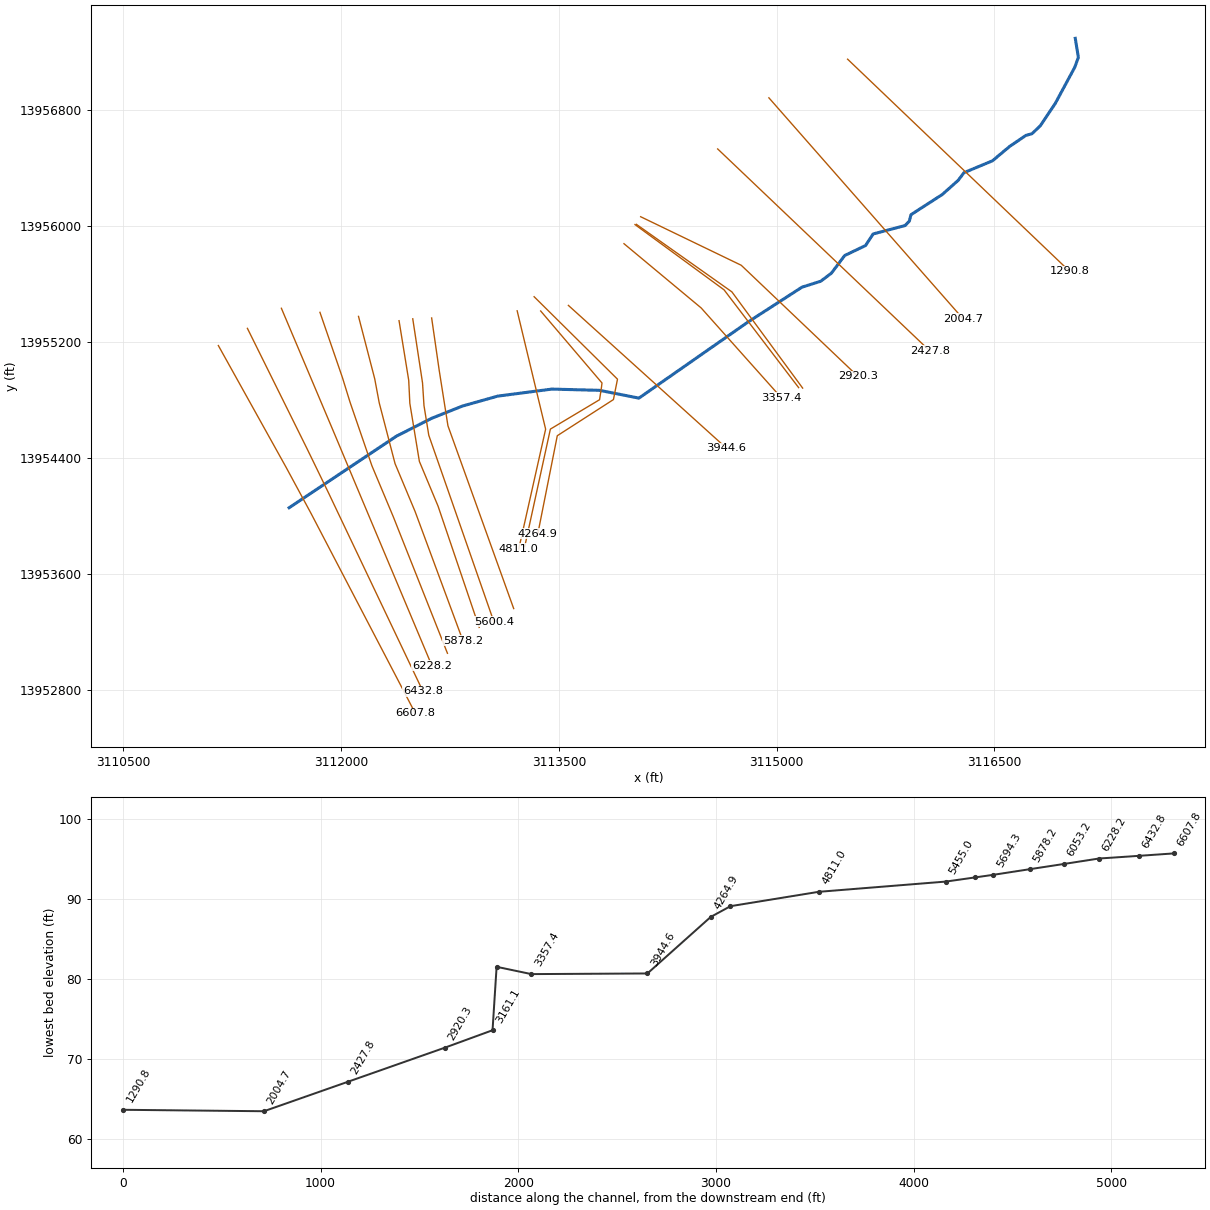
--- J109-00-00.prj (project) ---

Proj Title=J109-00-00
Current Plan=p01
Default Exp/Contr=.3,.1
English Units
Geom File=g01
Flow File=f01
Flow File=f02
Plan File=p01
Plan File=p02
Y Axis Title=Elevation
X Axis Title(PF)=Main Channel Distance
X Axis Title(XS)=Station
BEGIN DESCRIPTION:
END DESCRIPTION:
DSS File=dss
DSS Export Rating Curves= 0
DSS Export Rating Curve Sorted= 0
DSS Export Volume Flow Curves= 0
DXF OffsetX= 0
DXF OffsetY= 0
DXF ScaleX= 1
DXF ScaleY= 10

--- J109-00-00.p01 (plan) ---

Plan Title=Effective Multi-Profile 2015
Version=Version 3.0.1  May 2012
Short Identifier=Eff+LOMR MP
Geom File=g01
Flow File=f01
Subcritical Flow
K Sum by GR= 0
Std Step Tol= 0.01
Critical Tol= 0.01
Num of Std Step Trials= 20
Max Error Tol= 0.3
Flow Tol Ratio= 0.001
Split Flow NTrial= 30
Split Flow Tol= 0.02
Split Flow Ratio= 0.02
Log Output Level= 0
Friction Slope Method= 1
Unsteady Friction Slope Method= 2
Parabolic Critical Depth
Global Vel Dist= 0 , 0 , 0
Global Log Level= 0
CheckData=True
Encroach Param=-1 ,0,0, 0
BEGIN DESCRIPTION:
FEMA Effective Multi-Profile June 2007 + LOMR 14-06-1809P
END DESCRIPTION:
Computation Interval=1HOUR
Output Interval=1HOUR
Run HTab= 0
Run UNet= 0
Run PostProcess= 0
UNET Theta= 1
UNET ZTol= 0.02
UNET ZSATol= 0.05
UNET MxIter= 20
UNET MaxInSteps= 0
UNET DtIC= 0
UNET DtMin= 0
UNET MaxCRTS= 20
UNET WFStab= 2
UNET SFStab= 1
UNET WFX= 1
UNET SFX= 1
UNET Convert EG Bridges= 0
UNET Use Existing IB Tables=-1
Instantaneous Interval=1HOUR
Write IC File= 0
IC Time=0
Write Velocity= 0
Write Detailed= 0

--- J109-00-00.p02 (plan) ---

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Plan Title=Effective FW 2015
Short Identifier=Eff+LOMR FW
Geom File=g01
Flow File=f02
Encroach Param=-1 ,0,0, 2
Encroach River=J109-00-00
Encroach Reach=J109-00-00_0013
Encroach Node=6607.8
       1  4968.8  5028.8
Encroach Node=6432.8
       1    4957 5030.83
Encroach Node=6228.2
       1  4943.2  5033.2
Encroach Node=6053.2
       1 4910.33 5038.93
Encroach Node=5878.2
       1 4910.07 5046.03
Encroach Node=5694.3
       1  685.95  793.85
Encroach Node=5671.95
       1  685.95  793.85
Encroach Node=5600.4
       1   638.5  760.09
Encroach Node=5455.0
       1  4954.9  5044.9
Encroach Node=4811.0
       1  4955.1  5045.1
Encroach Node=4364.8
       1  4964.5    5052
Encroach Node=4264.9
       1 4965.99    5100
Encroach Node=3944.6
       1  4958.6    5052
Encroach Node=3357.4
       1  4958.6  5035.4
Encroach Node=3181.7
       1  4974.3  5037.3
Encroach Node=3161.1
       1  4967.2  5032.4
Encroach Node=2920.3
       1  4967.2  5032.4
Encroach Node=2427.8
       1  4966.8  5034.4
Encroach Node=2004.7
       1  4947.9    5150
Encroach Node=1290.8
       1  4953.3  5095.6
FEMA Effective Floodway June 2007 + LOMR 14-06-1809P

--- J109-00-00.f01 (steady flow) ---

Flow Title=FEMA Effective 2015
Version=Version 3.0.1  May 2012
Number of Profiles= 4
Profile Names=10PCT_10yr, 2PCT_50yr, 1PCT_100yr, 0.2PCT_500yr
River Rch & RM=J109-00-00,J109-00-00_0013 ,6607.8
     490     740     850    1280
River Rch & RM=J109-00-00,J109-00-00_0013 ,6228.2
     520     780     900    1360
River Rch & RM=J109-00-00,J109-00-00_0013 ,5878.2
     550     820     950    1440
River Rch & RM=J109-00-00,J109-00-00_0013 ,5455.0
     600     900    1050    1600
River Rch & RM=J109-00-00,J109-00-00_0013 ,4364.8
     600     900    1050    1600
River Rch & RM=J109-00-00,J109-00-00_0013 ,3944.6
     960    1470    1690    2300
River Rch & RM=J109-00-00,J109-00-00_0013 ,3357.4
     990    1500    1750    2400
River Rch & RM=J109-00-00,J109-00-00_0013 ,2427.8
    1700    2420    2780    3930
River Rch & RM=J109-00-00,J109-00-00_0013 ,2004.7
    1691    2536    2921    4087
Boundary for River Rch & Prof#=J109-00-00,J109-00-00_0013 , 1
Up Type= 0
Dn Type= 3
Dn Slope=.005
Boundary for River Rch & Prof#=J109-00-00,J109-00-00_0013 , 2
Up Type= 0
Dn Type= 3
Dn Slope=.005
DSS Import GetInterval= 0
DSS Import GetPeak= 0
DSS Import FillOption= 0

--- J109-00-00.f02 (steady flow) ---

Flow Title=Effective FW 2015
Version=Version 3.0.1  May 2012
Number of Profiles= 2
Profile Names=1PCT_100yr, 1PCTFloodway_100yrFW
River Rch & RM=J109-00-00,J109-00-00_0013 ,6607.8
     850     850
River Rch & RM=J109-00-00,J109-00-00_0013 ,6228.2
     900     900
River Rch & RM=J109-00-00,J109-00-00_0013 ,5878.2
     950     950
River Rch & RM=J109-00-00,J109-00-00_0013 ,5455.0
    1050    1050
River Rch & RM=J109-00-00,J109-00-00_0013 ,3944.6
    1690    1690
River Rch & RM=J109-00-00,J109-00-00_0013 ,3357.4
    1750    1750
River Rch & RM=J109-00-00,J109-00-00_0013 ,2427.8
    2780    2780
River Rch & RM=J109-00-00,J109-00-00_0013 ,2004.7
    2921    2921
Boundary for River Rch & Prof#=J109-00-00,J109-00-00_0013 , 1
Up Type= 0
Dn Type= 3
Dn Slope=.005
Boundary for River Rch & Prof#=J109-00-00,J109-00-00_0013 , 2
Up Type= 0
Dn Type= 1
Dn Known WS=74.33
DSS Import GetInterval= 0
DSS Import GetPeak= 0
DSS Import FillOption= 0

--- J109-00-00.g01 (geometry) ---

Geom Title=J109-00-00 2015
Version=Version 3.0.1  May 2012

River Reach=J109-00-00      ,J109-00-00_0013
Reach XY= 30
      3111642.19   13954055.4811    3112380.6117   13954549.0085
    3112622.7623   13954672.2866    3112835.4409   13954757.1674
    3113078.6386   13954825.8349    3113451.5416   13954874.4744
    3113780.5736    13954865.891    3114051.8588   13954812.0689
    3114801.7918   13955336.4903    3115174.9236   13955577.8682
    3115304.4453   13955619.0996    3115377.6748    13955674.555
    3115469.3895   13955796.4858    3115613.0048   13955865.4495
    3115665.2609   13955945.4333    3115885.3051   13956003.3771
    3115914.8102   13956034.3041    3115925.8302   13956078.3841
    3116140.8445   13956217.0999    3116250.9839   13956315.2834
    3116291.2294   13956368.5944    3116486.8415   13956450.0592
    3116606.3472   13956550.0905    3116717.4583   13956625.6113
        3116759.       13956637.      3116816.75       13956692.
    3116919.7152   13956846.0974    3117053.3958   13957094.3613
        3117079.       13957164.    3117057.7361   13957295.7502

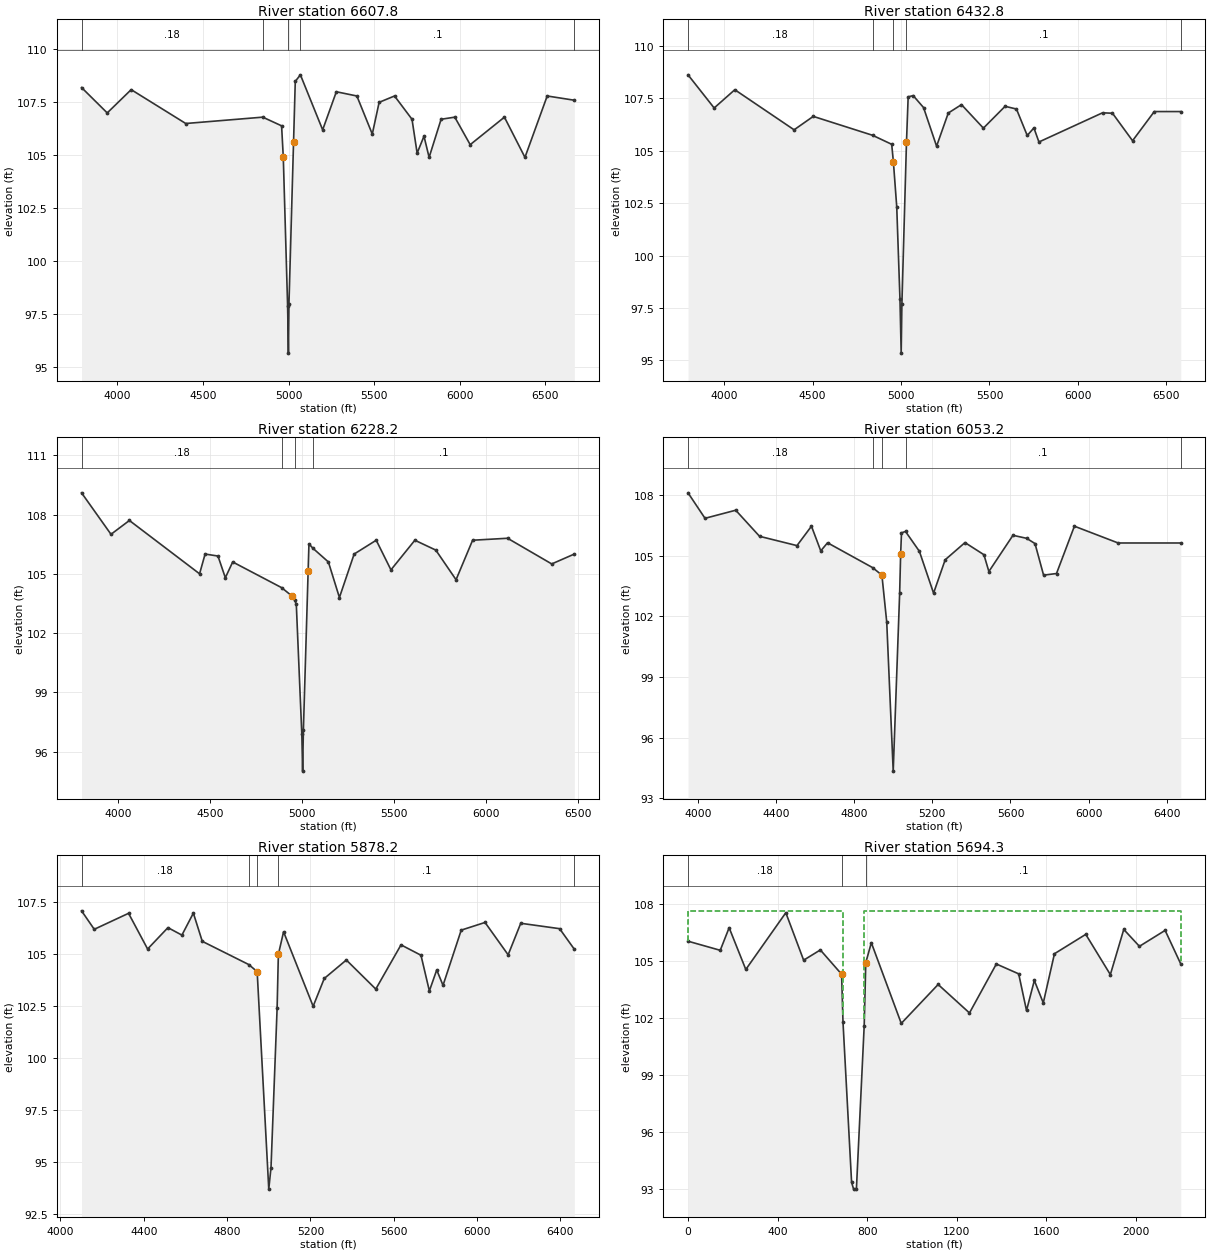
Type RM Length L Ch R = 1 ,6607.8  ,191.28,175,163.16
BEGIN DESCRIPTION:
Cross Section Xs09
END DESCRIPTION:
XS GIS Cut Line= 4
    3111154.6951   13955175.0954     3111619.568   13954337.9255
     3111792.149   13954018.2585    3112511.7302    13952635.932
#Sta/Elev= 30
    3790   108.2    3940     107    4080   108.1  4398.8   106.5  4848.8   106.8
  4958.9  106.39  4968.8104.9045  4994.1   97.87  4998.8   95.65  5001.8   97.95
  5028.8105.6413  5038.8  108.49  5068.8   108.8  5198.8   106.2  5278.8     108
  5398.8   107.8  5488.8     106  5528.8   107.5  5618.8   107.8  5720.9   106.7
  5750.9   105.1  5790.9   105.9  5820.9   104.9  5890.9   106.7  5970.9   106.8
  6060.9   105.5  6260.9   106.8  6380.9   104.9  6510.9   107.8  6669.3   107.6
#Mann= 5 ,-1 , 0
    3790     .18       0  4848.8     .08       0  4998.8     .05       0
  5068.8      .1       0  6669.3      .2       0
#Block Obstruct= 2 , 0
       0                    5100       0   108.5
Bank Sta=4968.8,5028.8
XS Rating Curve= 0
Exp/Cntr=.3,.1

Type RM Length L Ch R = 1 ,6432.8  ,223.64,204.6,190.76
XS GIS Cut Line= 6
  3111354.889933 13955293.729401 3111765.060801813954464.2162424
 3111800.847115813954390.6238452 3111918.273386313954148.2574387
 3111952.457448413954076.1647745 3112564.559361413952787.0049428
#Sta/Elev= 30
 3795.44  108.61 3943.25  107.03 4060.03   107.9 4395.34  105.99 4503.73  106.63
 4838.75  105.73 4947.24   105.3    4957  104.44  4975.7  102.32 4993.96   97.92
 5000.83   95.35 5004.93   97.71 5030.83  105.41 5040.28  107.56 5068.65  107.62
 5127.33  107.05 5201.02  105.21  5267.2  106.79 5341.79  107.19 5465.75  106.07
 5588.42  107.11 5652.75  106.98 5713.56  105.72 5751.38  106.08 5779.75  105.41
 6139.36   106.8 6195.76  106.78 6309.21  105.47 6432.13  106.86 6581.89  106.86
#Mann= 5 ,-1 , 0
 3795.44     .18       0 4838.75     .08       0    4957     .05       0
 5030.83      .1       0 6581.89    .154       0
#Block Obstruct= 2 , 0
       0                 5071.23       0  107.53
Bank Sta=4957,5030.83
XS Rating Curve= 0
Exp/Cntr=.3,.1

Type RM Length L Ch R = 1 ,6228.2  ,183.33,175,167.17
BEGIN DESCRIPTION:
Cross Section Xs08.5
END DESCRIPTION:
XS GIS Cut Line= 4
    3111588.9463   13955432.4295    3111965.7697    13954539.327
     3112095.335   13954229.4389    3112626.3242   13952963.6308
#Sta/Elev= 30
  3801.8   109.1  3961.8     107  4061.8   107.7  4443.2     105  4473.2     106
  4543.2   105.9  4583.2   104.8  4623.2   105.6  4888.9   104.3  4943.2103.8918
  4959.5  103.67  4968.8  103.47  4998.9   96.87  5003.2   95.01  5007.3   97.07
  5033.2105.1478  5037.6  106.52  5058.3   106.3  5143.2   105.6  5203.2   103.8
  5283.2     106  5403.2   106.7  5483.2   105.2  5613.2   106.7    5727   106.2
    5837   104.7    5927   106.7    6117   106.8    6357   105.5  6479.7     106
#Mann= 4 ,-1 , 0
  3801.8     .18       0  4888.9     .08       0  4959.5     .05       0
  5058.3      .1       0
#Block Obstruct= 2 , 0
       0                  5037.6       0   106.4
Bank Sta=4943.2,5033.2
XS Rating Curve= 0
Exp/Cntr=.3,.1

Type RM Length L Ch R = 1 ,6053.2  ,183.33,175,167.2
XS GIS Cut Line= 6
  3111854.60817413955404.3117684 3112009.010022613954955.2882859
 3112062.178524513954783.1286574 3112212.315856413954345.7095292
 3112360.450336613953991.6459951 3112732.917880513953050.7630787
#Sta/Elev= 30
 3950.03   108.1 4036.95  106.84 4194.04  107.24 4316.04  105.95 4507.54  105.49
 4581.67  106.45 4629.23  105.23    4664  105.63 4894.94   104.4 4942.14  104.03
 4966.83  101.71    5000   94.34 5033.04  103.16 5038.01  105.07 5042.37  106.12
 5062.88  106.19 5133.85  105.21 5206.47  103.14 5265.93  104.79 5367.25  105.64
 5464.13  105.04 5489.51  104.21 5612.77     106 5682.95  105.85 5725.54  105.59
 5769.43  104.03 5835.55  104.11 5927.12  106.45 6150.96  105.62 6471.44  105.62
#Mann= 5 ,-1 , 0
 3950.03     .18       0 4894.94     .08       0 4942.14     .05       0
 5062.88      .1       0 6471.44      .1       0
#Block Obstruct= 2 , 0
 1394.37                 5063.68 1394.37  105.85
Bank Sta=4942.14,5038.01
XS Rating Curve= 0
Exp/Cntr=.3,.1

Type RM Length L Ch R = 1 ,5878.2  ,192.66,183.9,175.67
XS GIS Cut Line= 6
  3112120.27004913955376.1940368 3112231.888073413954945.4933578
 3112262.890465413954779.7233364 3112371.818638513954360.2782461
 3112510.526377613954028.0915721  3112839.51156113953137.8953575
#Sta/Elev= 30
 4101.47  107.09 4162.44   106.2 4327.06  106.97 4418.51  105.25 4516.06  106.28
 4583.12  105.92 4638.07  106.98 4680.86  105.62  4904.2   104.5  4944.3  104.16
    5000   93.68 5010.72   94.72 5040.01  102.39 5046.03  104.99 5071.02  106.08
 5212.96  102.49 5266.26  103.83 5372.26  104.72 5513.61  103.32 5634.68  105.45
 5730.45  104.95 5770.78  103.23 5806.06  104.24  5836.3   103.5 5923.68  106.16
 6037.93  106.53 6148.83  104.97 6209.32  106.49 6395.82  106.23 6466.39  105.24
#Mann= 5 ,-1 , 0
 4101.47     .18       0  4904.2     .08       0  4944.3     .05       0
 5046.03      .1       0 6466.39      .1       0
#Block Obstruct= 2 , 0
 2791.95                 5092.98 2791.95  105.29
Bank Sta=4944.3,5046.03
XS Rating Curve= 0
Exp/Cntr=.3,.1

Type RM Length L Ch R = 1 ,5694.3  ,96.21,93.87,93.48
BEGIN DESCRIPTION:
XS 3 for Dual Bridge
END DESCRIPTION:
XS GIS Cut Line= 6
 3112399.442764913955346.6463138 3112466.101096213954935.2002863
 3112473.810070213954776.1448301 3112539.433298613954375.5878884
 3112668.234878213954066.3906722 3112951.526306413953229.4589471
#Sta/Elev= 30
       0  106.04   143.9  105.56   183.6  106.75  258.03  104.55  436.72  107.54
  516.34  105.04   590.9  105.58  685.95   104.3  692.02  101.79  730.44   93.34
   739.4   92.98  752.08   93.01  786.73  101.59  793.85  104.91   818.6  105.96
  952.25  101.71 1116.93  103.76 1256.91  102.26 1376.81  104.84 1476.65  104.32
 1511.59  102.39 1546.53  103.97 1586.47  102.79 1636.39  105.38 1776.16   106.4
 1885.99  104.28 1945.89  106.66 2015.78  105.77 2130.59  106.61 2200.48  104.84
#Mann= 3 , 0 , 0
       0     .18       0  685.95    .013       0  793.85      .1       0
#XS Ineff= 2 , 0
       0  691.36  107.64  787.48       0  107.64
Permanent Ineff=
       F       F
#Block Obstruct= 2 , 0
       0                  863.15       0  104.71
Bank Sta=685.95,793.85
XS Rating Curve= 0
Exp/Cntr=.5,.3

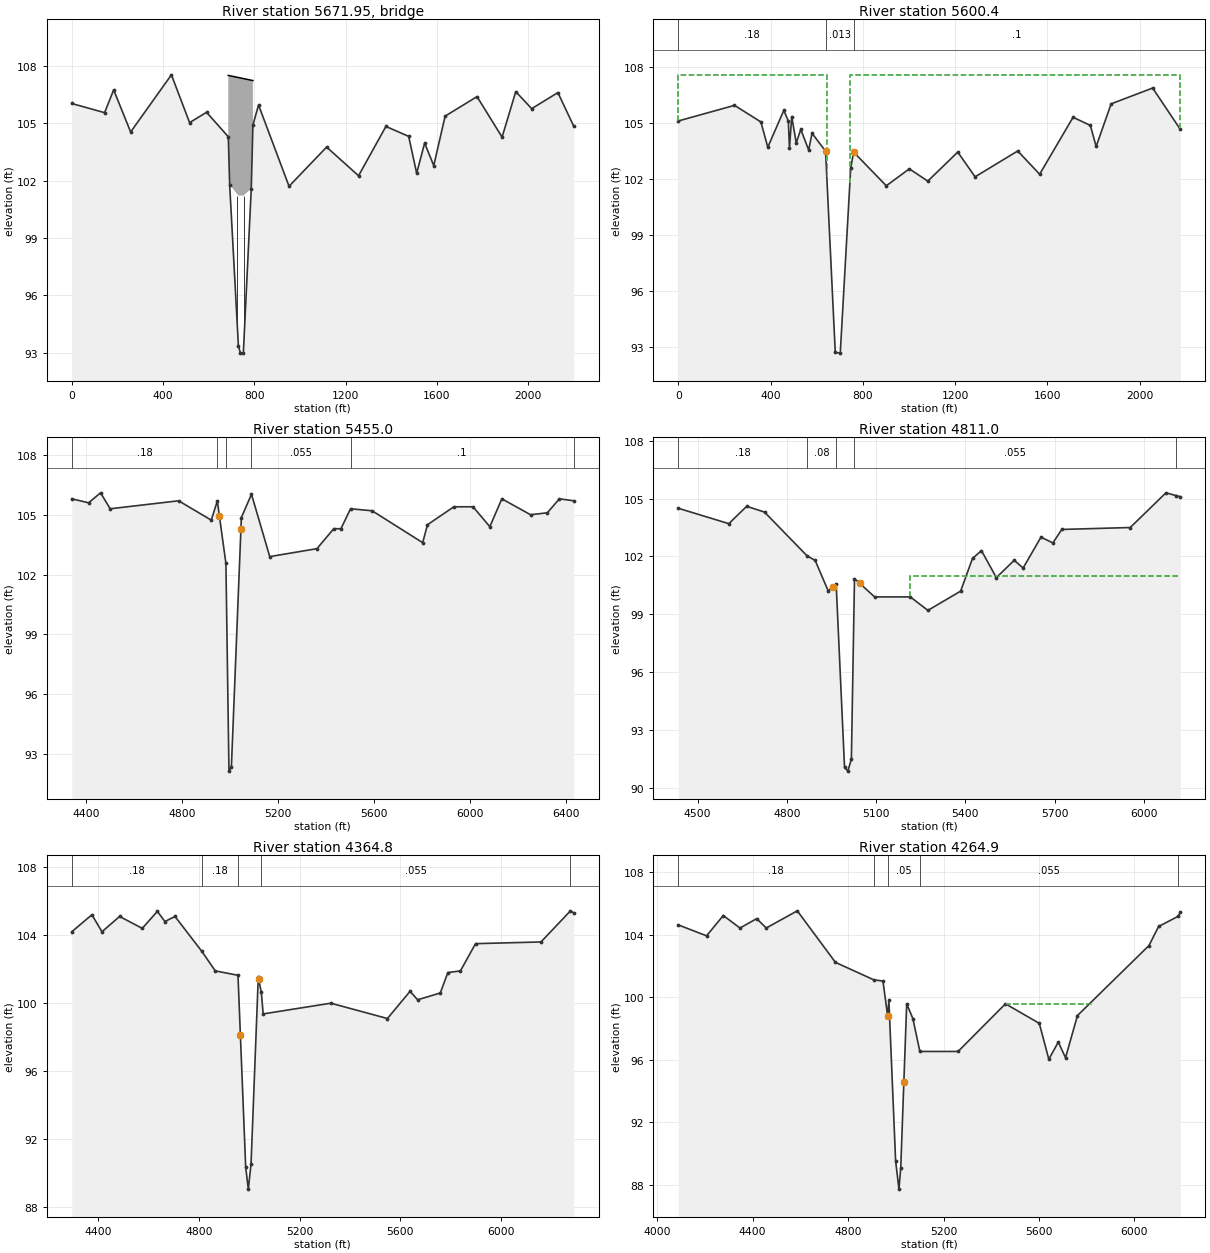
Type RM Length L Ch R = 3 ,5671.95 ,,,
BEGIN DESCRIPTION:
Dual Bridge
END DESCRIPTION:
Bridge Culvert--1,0,-1,-1, 0
Deck Dist Width WeirC Skew NumUp NumDn MinLoCord MaxHiCord MaxSubmerge Is_Ogee
5,83.76,2.6,0, 2, 2, , , .98, 0, 0,0,,
  685.95  793.85
  107.51  107.24
  101.22  101.22
   638.5  760.09
  107.45  107.18
  101.16  101.16
Pier Skew, UpSta & Num, DnSta & Num=  ,724.39, 2 ,668.5, 2 , 0 , 0 , 0 ,,
       2       2
      90     105
       2       2
      90     105
Pier Skew, UpSta & Num, DnSta & Num=  ,755.18, 2 ,699.29, 2 , 0 , 0 , 0 ,,
       2       2
      92     105
       2       2
      92     105
BR Coef=-1 , 0 , 0 ,, 0 ,,,.8,-1,,0,
WSPro=,,,, 1 ,,,, 0 ,,,, 0 ,,,,-1 ,-1 ,-1 , 0 , 0 , 0 , 0 , 0
BC Design=,, 0 ,, 0 ,,,,,,
BC HTab HWMax=107.54

Type RM Length L Ch R = 1 ,5600.4  ,148.74,145.43,144.84
BEGIN DESCRIPTION:
XS 2 for Dual Bridge
END DESCRIPTION:
XS GIS Cut Line= 5
   3112493.93503 13955359.580343 3112561.277743113954916.8486169
 3112571.297736113954760.5694019 3112604.226804113954555.9083939
 3113052.962783313953267.5664824
#Sta/Elev= 30
       0  105.12  243.82  105.96  358.26  105.07  388.11  103.71  457.61  105.69
  477.19  105.12  482.08  103.66  491.87  105.36  511.44  103.94  531.02  104.67
  565.27  103.56  579.96  104.46   638.5   103.5  680.58   92.69  702.22   92.65
  747.56   102.6  760.09  103.45  901.67  101.64 1001.61  102.55 1081.57  101.89
  1211.5  103.45 1286.46  102.12 1471.36  103.51  1566.3  102.26 1711.22  105.32
 1786.18  104.88 1811.17  103.75 1876.13  106.04 2056.03  106.89 2175.97  104.67
#Mann= 3 , 0 , 0
       0     .18       0   638.5    .013       0  760.09      .1       0
#XS Ineff= 2 , 0
       0  643.84   107.6   743.8       0   107.6
Permanent Ineff=
       F       F
#Block Obstruct= 2 , 0
       0                   831.7       0  102.65
Bank Sta=638.5,760.09
XS Rating Curve= 0
Exp/Cntr=.5,.3

Type RM Length L Ch R = 1 ,5455.0  ,634.53,644,652.72
BEGIN DESCRIPTION:
XS 01 for Dual Bridge; Cross Section Xs07
END DESCRIPTION:
XS GIS Cut Line= 4
    3112624.0218   13955365.4549    3112676.1412   13955003.8358
    3112736.3886   13954620.8345    3113189.2425   13953359.2819
#Sta/Elev= 30
  4339.5   105.8  4409.6   105.6  4459.6   106.1  4499.6   105.3    4785   105.7
 4921.23  104.73 4946.42  105.69  4954.9104.9492 4982.25  102.56    4995   92.14
 5005.12   92.36  5044.9104.3073 5046.74  104.86 5088.83  106.03    5165   102.9
  5361.9   103.3  5431.9   104.3  5461.9   104.3  5501.9   105.3  5591.9   105.2
  5802.7   103.6  5822.7   104.5  5932.7   105.4  6012.7   105.4  6082.7   104.4
  6132.7   105.8  6252.7     105  6322.7   105.1  6372.7   105.8    6433   105.7
#Mann= 6 ,-1 , 0
  4339.5     .18       0 4946.42     .08       0 4982.25     .05       0
 5088.83    .055       0  5501.9      .1       0    6433      .2       0
#Block Obstruct= 2 , 0
       0                    5085       0   104.8
Bank Sta=4954.9,5044.9
XS Rating Curve= 0
Exp/Cntr=.3,.1

Type RM Length L Ch R = 1 ,4811.0  ,458,446.2,421
BEGIN DESCRIPTION:
Cross Section XS06
END DESCRIPTION:
XS GIS Cut Line= 3
    3113213.1144   13955414.8161    3113409.2234   13954597.6957
     3113224.192   13953771.0956
#Sta/Elev= 30
  4435.2   104.5  4605.2   103.7  4665.2   104.6  4725.2   104.3  4868.8  102.02
  4895.2   101.8 4939.26  100.21  4955.1100.4112 4966.03  100.55  4994.1   91.06
  5005.2   90.86 5017.11   91.48 5027.57  100.85  5045.1100.6038  5095.2    99.9
  5215.2    99.9  5274.3    99.2  5384.3   100.2  5424.3   101.9  5454.3   102.3
  5504.3   100.9  5564.3   101.8  5594.3   101.4  5654.3     103  5694.3   102.7
  5724.3   103.4  5954.3   103.5  6074.3   105.3  6107.7  105.16  6122.6   105.1
#Mann= 5 ,-1 , 0
  4435.2     .18       0  4868.8     .08       0 4966.03     .05       0
 5027.57    .055       0  6107.7      .2       0
#XS Ineff= 2 , 0
       0                    5215       0     101
Permanent Ineff=
       F       F
#Block Obstruct= 2 , 0
       0                    5225       0    99.5
Bank Sta=4955.1,5045.1
XS Rating Curve= 0
Exp/Cntr=.3,.1

Type RM Length L Ch R = 1 ,4364.8  ,117.02,99.9,68.03
BEGIN DESCRIPTION:
Cross Section XS05.5
END DESCRIPTION:
XS GIS Cut Line= 6
    3113375.0776   13955413.6338    3113797.4658   13954916.6823
    3113794.6249    13954892.456    3113780.7552   13954801.1263
    3113441.9675   13954598.2903    3113265.1216   13953786.8476
#Sta/Elev= 30
  4294.8   104.2  4374.8   105.2  4414.8   104.2  4484.8   105.1  4574.8   104.4
  4634.8   105.4  4664.8   104.8  4704.8   105.1  4810.8  103.06  4864.8   101.9
 4955.02  101.64  4964.598.14802 4985.67   90.35  4996.1   89.07  5006.9   90.55
 5035.59  101.52  5036.9 101.424 5047.73  100.63 5055.15   99.37  5323.8     100
  5548.6    99.1  5638.6   100.7  5668.6   100.2  5758.6   100.6  5788.6   101.8
  5838.6   101.9  5898.6   103.5  6158.6   103.6  6275.7  105.43  6289.1   105.3
#Mann= 5 ,-1 , 0
  4294.8     .18       0  4810.8     .18       0 4955.02    .013       0
 5047.73    .055       0  6275.7      .2       0
#Block Obstruct= 2 , 0
       0                    5345       0    99.6
Bank Sta=4964.5,5036.9
XS Rating Curve= 0
Exp/Cntr=.3,.1

Type RM Length L Ch R = 1 ,4264.9  ,186.24,320.3,630.71
BEGIN DESCRIPTION:
Upstream Section of Bridge/Culvert/Weir
END DESCRIPTION:
XS GIS Cut Line= 6
    3113329.9284   13955512.1931    3113904.2653   13954942.8488
    3113891.9716   13954881.2241    3113876.3674   13954802.1411
    3113489.5494   13954552.6417    3113355.2307   13953874.9711
#Sta/Elev= 30
  4088.7  104.64  4207.4  103.94  4277.4  105.24  4347.4  104.44  4417.4  105.04
  4457.4  104.44  4587.4  105.54  4747.4  102.24  4908.5  101.12  4946.3  101.05
 4965.99   98.81 4971.14   99.82 4999.38   89.53  5013.3   87.73 5020.81   89.09
 5033.8594.57346 5045.78   99.59  5071.7   98.64  5100.9   96.54  5260.9   96.54
 5459.55   99.59  5601.2   98.34  5641.2   96.04  5680.8   97.14  5711.2   96.14
  5761.2   98.84  6060.8  103.32  6101.2  104.54  6183.1  105.19    6192  105.44
#Mann= 5 ,-1 , 0
  4088.7     .18       0  4908.5     .08       0 4965.99     .05       0
  5100.9    .055       0  6183.1      .2       0
#XS Ineff= 1 ,-1
    5459  5820.8   99.59
Permanent Ineff=
       F
#Block Obstruct= 2 , 0
       0                    5525       0      99
Bank Sta=4965.99,5033.85
XS Rating Curve= 0
Exp/Cntr=.3,.1

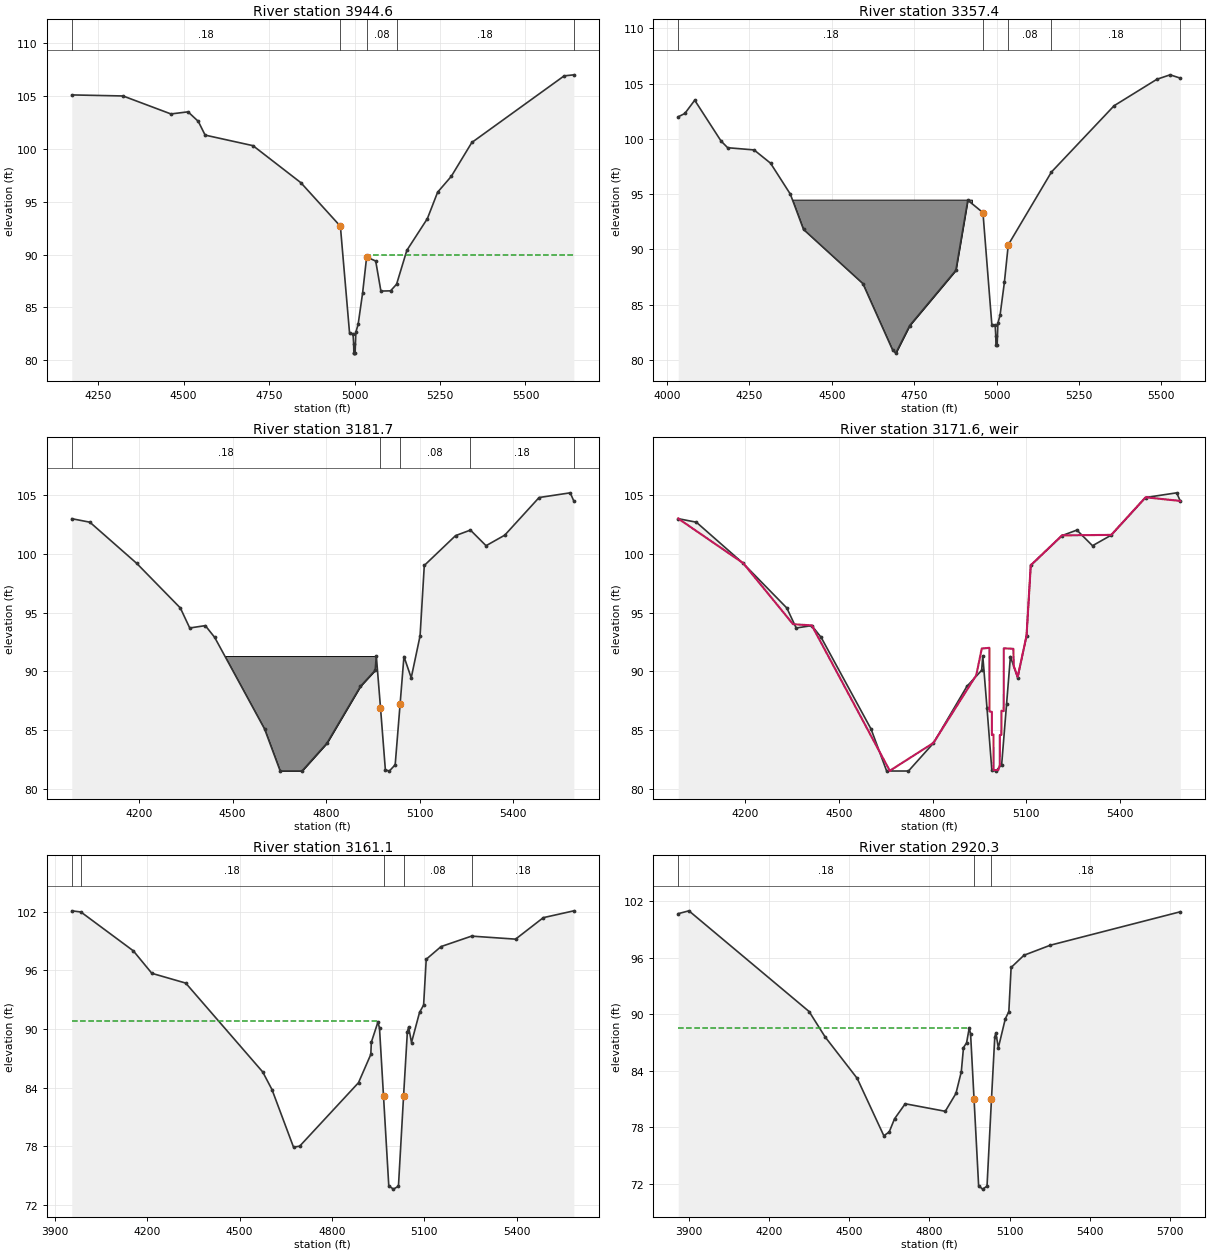
Type RM Length L Ch R = 1 ,3944.6  ,607.47,587.2,574.57
BEGIN DESCRIPTION:
Cross Section XS05
END DESCRIPTION:
XS GIS Cut Line= 2
    3113565.9764   13955452.2053    3114654.6303   13954466.8228
#Sta/Elev= 30
    4173   105.1    4323     105    4463   103.3    4513   103.5    4543   102.6
    4563   101.3    4703   100.3    4843    96.8  4958.6   92.68  4985.5   82.55
  4995.6   82.51  4997.5   81.52    4998   80.69  4999.8   80.68  5001.7   80.73
  5003.9   82.66  5010.6   83.42  5023.6   86.36  5035.4   89.77  5061.9   89.39
  5077.1   86.55  5105.4   86.57    5123    87.2    5153    90.4    5213    93.4
    5243    95.9    5283    97.4    5343   100.6    5613   106.9  5641.4     107
#Mann= 5 ,-1 , 0
    4173     .18       0  4958.6     .05       0  5035.4     .08       0
    5123     .18       0  5641.4      .2       0
#XS Ineff= 2 , 0
       0                  5035.4       0      90
Permanent Ineff=
       F       F
Bank Sta=4958.6,5035.4
XS Rating Curve= 0
Exp/Cntr=.3,.1

Type RM Length L Ch R = 1 ,3357.4  ,141.47,175.75,126.63
BEGIN DESCRIPTION:
Cross Section XS04
END DESCRIPTION:
XS GIS Cut Line= 3
    3113948.9416   13955878.2003    3114480.4449   13955434.8257
     3115033.025   13954814.3054
#Sta/Elev= 30
  4034.2     102  4054.2   102.3  4084.2   103.5  4164.2    99.8  4184.2    99.2
  4264.2      99  4314.2    97.8  4374.2      95  4414.2    91.8  4594.2    86.9
  4684.2    80.9  4694.2    80.6  4736.4    83.1  4876.4    88.1  4912.6   94.45
  4958.6   93.32  4985.5   83.19  4995.6   83.15  4997.5   82.16    4998   81.33
  5001.7   81.37  5003.9    83.3  5010.6   84.06  5023.6      87  5035.4   90.41
  5166.4      97  5356.4     103  5486.4   105.4  5526.4   105.8  5557.3   105.5
#Mann= 5 ,-1 , 0
  4034.2     .18       0  4958.6     .05       0  5035.4     .08       0
  5166.4     .18       0  5557.3      .2       0
#Block Obstruct= 2 , 0
       0    4925    94.5               0
Bank Sta=4958.6,5035.4
XS Rating Curve= 0
Exp/Cntr=.5,.3

Type RM Length L Ch R = 1 ,3181.7  ,20.55,20.55,20.55
BEGIN DESCRIPTION:
Upstream Section of Bridge/Culvert/Weir
END DESCRIPTION:
XS GIS Cut Line= 3
    3114024.8747    13956010.048    3114638.4852   13955559.5041
     3115152.121   13954884.5613
#Sta/Elev= 30
  3984.7  102.99  4042.8  102.69  4192.8   99.19  4332.8   95.39  4362.8   93.69
  4412.8   93.89  4442.8   92.89  4602.8   85.09  4652.8   81.52  4722.7   81.52
  4802.7   83.89  4910.2   88.73  4957.3   90.09  4960.9   91.32  4974.3   86.92
  4989.9   81.63  5002.4   81.51  5021.4   82.05  5037.3   87.26  5049.5   91.26
  5072.8   89.45  5101.2   93.02  5114.7   99.01    5215  101.55  5262.6  102.02
  5312.7  100.69  5372.7  101.59  5482.7  104.79  5582.4  105.19  5594.1  104.49
#Mann= 5 ,-1 , 0
  3984.7     .18       0  4974.3     .03       0  5037.3     .08       0
  5262.6     .18       0  5594.1      .2       0
#XS Ineff= 2 , 0
       0                    5050       0    91.2
Permanent Ineff=
       F       F
#Block Obstruct= 2 , 0
       0    4960    91.3               0
Bank Sta=4974.3,5037.3
XS Rating Curve= 0
Exp/Cntr=.5,.3

Type RM Length L Ch R = 5 ,3171.6  ,,,
BEGIN DESCRIPTION:
FND 80D NAIL
Structure ID: J109-00-00-S03
END DESCRIPTION:
IW Pilot Flow=0
#Inline Weir SE= 30
  3984.7     103  4192.8   99.21  4352.8   94.01  4412.8   93.91  4662.8   81.54
  4802.7   83.91  4940.2   89.68  4957.6   91.94  4982.3      92  4982.5   86.58
    4990   86.56  4990.1   84.58  4995.3   84.62  4995.4    81.6  5010.5    81.6
  5015.4   82.02  5015.6   84.58  5020.6   84.59  5020.7   86.65  5027.9   86.61
  5028.2   91.96  5058.9   91.92  5060.2   90.45  5072.8   89.53  5101.2   93.04
  5114.7   99.03    5215  101.57  5372.7  101.61  5482.7  104.81  5594.1   104.5
IW Dist,WD,Coef,Skew,MaxSub,Min_El,Is_Ogee,SpillHt,DesHd
10,.1,3,0,.95,, 0 ,,,5,5,

Type RM Length L Ch R = 1 ,3161.1  ,230,240.8,250
BEGIN DESCRIPTION:
Cross Section FIELD_DS
Located At: Drop Structure
END DESCRIPTION:
XS GIS Cut Line= 3
    3114034.4292   13956011.7289    3114692.3383   13955545.5284
    3115179.6991   13954881.3376
#Sta/Elev= 30
    3955   102.1  3984.7  101.98    4155      98    4215    95.7    4325    94.7
    4575    85.6    4605    83.8    4675    77.9    4695      78    4886    84.5
    4926    87.4  4927.6   88.64  4949.2   90.72  4954.2   90.08  4967.2   83.13
  4984.3   73.94  4999.4    73.6  5015.7    73.9  5032.4   83.17  5044.7   89.73
  5048.8   90.19  5058.1   88.61  5084.2    91.7  5097.4   92.45  5105.9   97.14
  5154.1   98.44  5253.1   99.51    5396    99.2    5486   101.4  5585.2   102.1
#Mann= 5 ,-1 , 0
    3955      .2       0  3984.7     .18       0  4967.2     .05       0
  5032.4     .08       0  5253.1     .18       0
#XS Ineff= 2 , 0
       0  4948.5    90.8               0
Permanent Ineff=
       F       F
Bank Sta=4967.2,5032.4
XS Rating Curve= 0
Exp/Cntr=.5,.3

Type RM Length L Ch R = 1 ,2920.3  ,470.67,492.5,490.82
BEGIN DESCRIPTION:
Cross Section XS03
END DESCRIPTION:
XS GIS Cut Line= 3
    3114063.7451   13956064.4047    3114756.7349   13955729.2332
    3115559.8574   13954962.9739
#Sta/Elev= 30
  3859.6   100.7  3899.6     101  4349.6    90.3  4409.6    87.6  4529.6    83.2
  4629.4    77.1  4649.4    77.5  4669.4    78.9  4709.4    80.5  4859.4    79.7
  4899.4    81.6  4919.4    83.9  4927.6   86.47  4939.2   86.98  4949.2   88.56
  4954.2   87.92  4967.2   80.96  4984.3   71.78  4999.4   71.43  5015.7   71.74
  5032.4      81  5044.7   87.57  5048.8   88.03  5058.1   86.45  5084.2   89.53
  5097.4   90.29  5105.9   94.98  5154.1   96.28  5253.1   97.35  5739.4   100.9
#Mann= 3 ,-1 , 0
  3859.6     .18       0  4967.2     .05       0  5032.4     .18       0
#XS Ineff= 2 , 0
       0    4949    88.6               0
Permanent Ineff=
       F       F
Bank Sta=4967.2,5032.4
XS Rating Curve= 0
Exp/Cntr=.3,.1

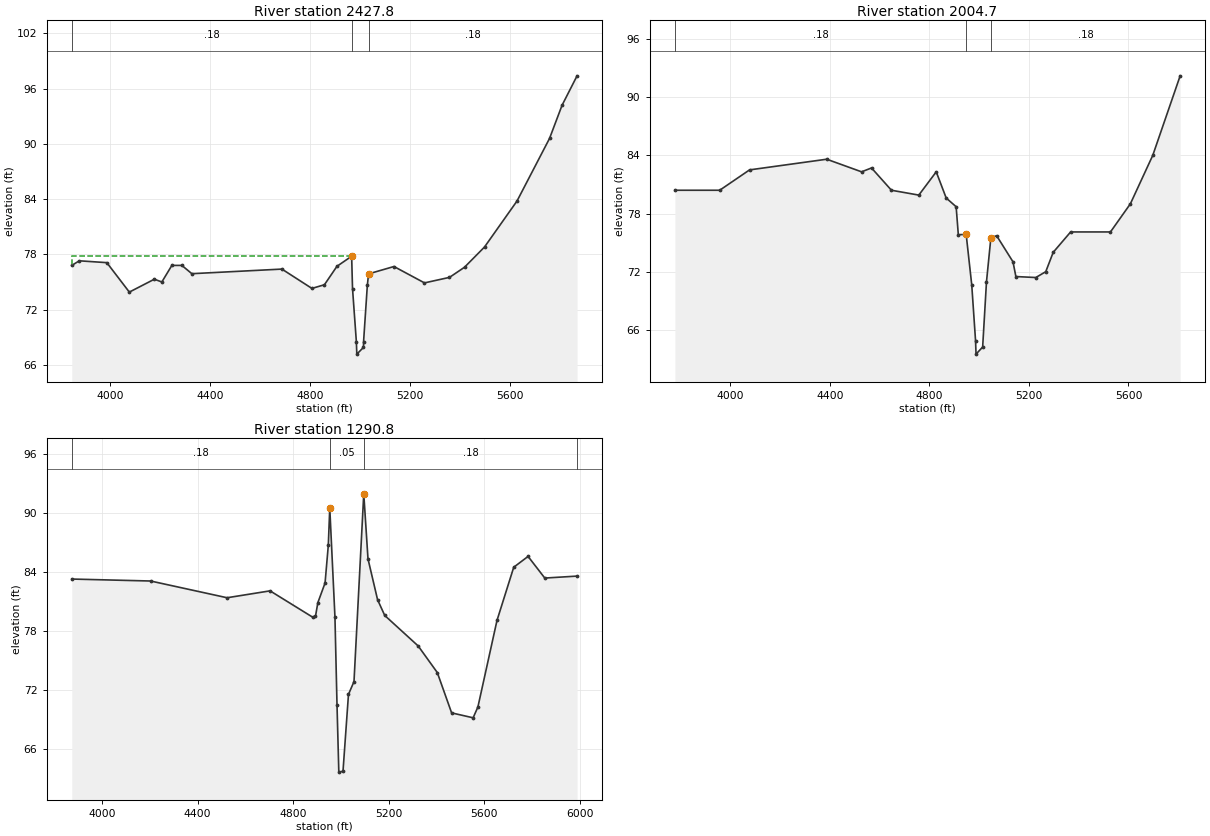
Type RM Length L Ch R = 1 ,2427.8  ,489.68,423.1,385.81
BEGIN DESCRIPTION:
Cross Section XS02.5
END DESCRIPTION:
XS GIS Cut Line= 2
    3114594.3886   13956532.2533    3116055.7914   13955137.8151
#Sta/Elev= 30
    3848    76.8    3878    77.3    3988    77.1    4078    73.9    4178    75.3
    4208      75    4248    76.8    4288    76.8    4328    75.9    4688    76.4
    4808    74.3    4858    74.7    4908    76.7  4966.8    77.8  4970.3   74.29
  4985.6   68.53  4987.5   67.16  5014.1   67.89  5014.5   68.52  5029.5   74.62
  5034.4   75.88    5136   76.68    5258    74.9    5358    75.5    5418    76.6
    5498    78.8    5628    83.8    5758    90.6    5808    94.2    5868    97.4
#Mann= 3 ,-1 , 0
    3848     .18       0  4966.8     .05       0  5034.4     .18       0
#XS Ineff= 2 , 0
       0  4966.8    77.8               0
Permanent Ineff=
       F       F
Bank Sta=4966.8,5034.4
XS Rating Curve= 0
Exp/Cntr=.3,.1

Type RM Length L Ch R = 1 ,2004.7  ,684.47,713.9,716.96
BEGIN DESCRIPTION:
Cross Section XS02
END DESCRIPTION:
XS GIS Cut Line= 2
     3114947.233   13956885.0977    3116285.5921   13955358.7668
#Sta/Elev= 30
  3777.6    80.4  3957.6    80.4  4077.6    82.5  4387.6    83.6  4527.6    82.3
  4567.6    82.7  4647.6    80.4  4757.6    79.9  4827.6    82.3  4867.6    79.6
  4907.6    78.7  4916.3   75.82  4947.9   75.84  4970.3   70.63  4985.6   64.87
  4987.5    63.5  5014.1   64.23  5029.5   70.96  5047.2   75.51  5070.3   75.71
    5136   73.02  5147.6    71.5  5227.6    71.4  5267.6      72  5297.6      74
  5367.6    76.1  5527.6    76.1  5607.6      79  5697.6      84  5807.6    92.2
#Mann= 3 ,-1 , 0
  3777.6     .18       0  4947.9     .05       0  5047.2     .18       0
Bank Sta=4947.9,5047.2
XS Rating Curve= 0
Exp/Cntr=.3,.1

Type RM Length L Ch R = 1 ,1290.8  ,1290.8,1290.8,1290.8
BEGIN DESCRIPTION:
Cross Section XS01
END DESCRIPTION:
XS GIS Cut Line= 2
    3115489.4085   13957151.8825    3117016.9665   13955688.8692
#Sta/Elev= 30
  3873.4    83.3  4203.4    83.1  4523.4    81.4  4703.4    82.1  4883.4    79.4
  4893.4    79.5  4903.4    80.9  4933.6    82.9  4947.1   86.71  4953.3   90.52
    4975   79.43  4983.6   70.49  4991.2   63.68  5008.7   63.77  5031.6   71.58
  5054.7   72.88  5095.6   91.96  5113.3   85.35  5153.4    81.2  5183.4    79.6
  5323.4    76.5  5403.4    73.8  5463.4    69.7  5553.4    69.2  5573.4    70.3
  5653.4    79.1  5723.4    84.5  5783.4    85.6  5853.4    83.4  5988.5    83.6
#Mann= 4 ,-1 , 0
  3873.4     .18       0  4953.3     .05       0  5095.6     .18       0
  5988.5      .2       0
Bank Sta=4953.3,5095.6
XS Rating Curve= 0
Exp/Cntr=.3,.1

Chan Stop Cuts=-1